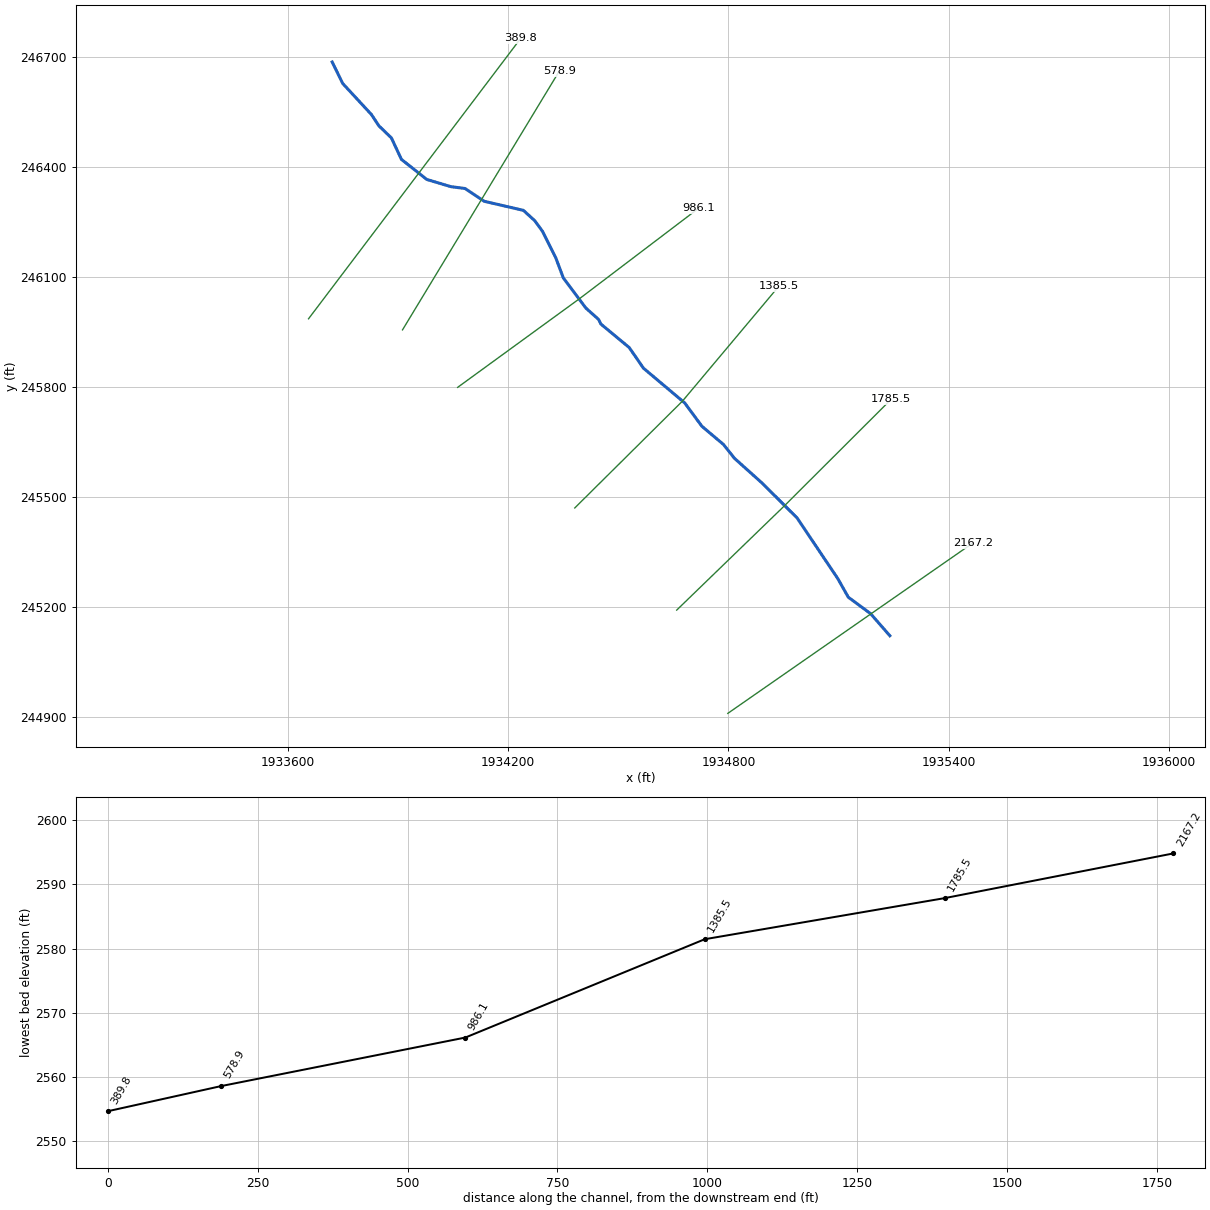
--- NP186.prj (project) ---

Proj Title=NP186
Current Plan=p01
Default Exp/Contr=0,0
English Units
Geom File=g01
Flow File=f01
Plan File=p01
BEGIN DESCRIPTION:
END DESCRIPTION:
DSS Export Rating Curves= 0
DSS Export Rating Curve Sorted= 0
DSS Export Volume Flow Curves= 0
DXF OffsetX= 0
DXF OffsetY= 0
DXF ScaleX= 0
DXF ScaleY= 0

--- NP186.p01 (plan) ---

Plan Title=Floodplain
Program Version=4.00
Geom File=g01
Flow File=f01
K Sum by GR=0
Std Step Tol=0.01
Critical Tol=0.01
Num of Std Step Trials=20
Max Error Tol=0.3
Flow Tol Ratio=0.001
Split Flow NTrial=30
Split Flow Tol=0.02
Split Flow Ratio=0.02
Log Output Level=0
Friction Slope Method=1
Unsteady Friction Slope Method=2
Unsteady Bridges Friction Slope Method=1
Global Log Level=0
CheckData=False
Run HTab=0
Run UNet=0
Run PostProcess=0
UNET Theta=0
UNET Theta Warmup=0
UNET ZTol=0
UNET ZSATol=0
UNET MxIter=0
UNET MaxInSteps=0
UNET DtIC=0
UNET DtMin=0
UNET MaxCRTS=0
UNET WFStab=0
UNET SFStab=0
UNET WFX=0
UNET SFX=0
UNET DSS MLevel=0
UNET DZMax Abort=0
UNET Convert EG Bridges=0
UNET Use Existing IB Tables=0
UNET Froude Limit=0
UNET Froude Power=0
Write IC File=0
Echo Input=False
Echo Output=False
Write Detailed=0

--- NP186.f01 (steady flow) ---

Flow Title=NFF Regression Equation
Program Version=4.00
Number of Profiles=1
Profile Names=P100yr
River Rch & RM=NP186,Main      ,2167.2
517.1070
River Rch & RM=NP186,Main      ,389.8
551.9811
Boundary for River Rch & Prof#=NP186,Main      ,1
Up Type=0
Dn Type=3
Dn Slope=0.024794

--- NP186.g01 (geometry) ---

Geom Title=USGS 3m DEM
Program Version=4.00

River Reach=NP186     ,Main
Reach XY= 30
     1935239.308      245121.458     1935186.837      245181.703
     1935126.205      245226.548     1935097.550      245277.348
     1934986.835      245442.775     1934893.052      245536.560
     1934816.202      245605.597     1934786.244      245643.371
     1934727.629      245692.869     1934680.738      245756.695
     1934568.531      245851.405     1934529.644      245907.794
     1934452.690      245971.758     1934446.410      245984.317
     1934411.480      246015.665     1934350.347      246097.647
     1934329.808      246152.419     1934293.531      246224.972
     1934272.802      246253.475     1934241.708      246281.978
     1934135.211      246306.658     1934082.873      246341.552
     1934043.796      246346.763     1933978.669      246366.302
     1933909.634      246421.010     1933882.281      246479.626
     1933848.106      246512.751     1933827.814      246543.565
     1933749.688      246628.200     1933721.043      246686.794

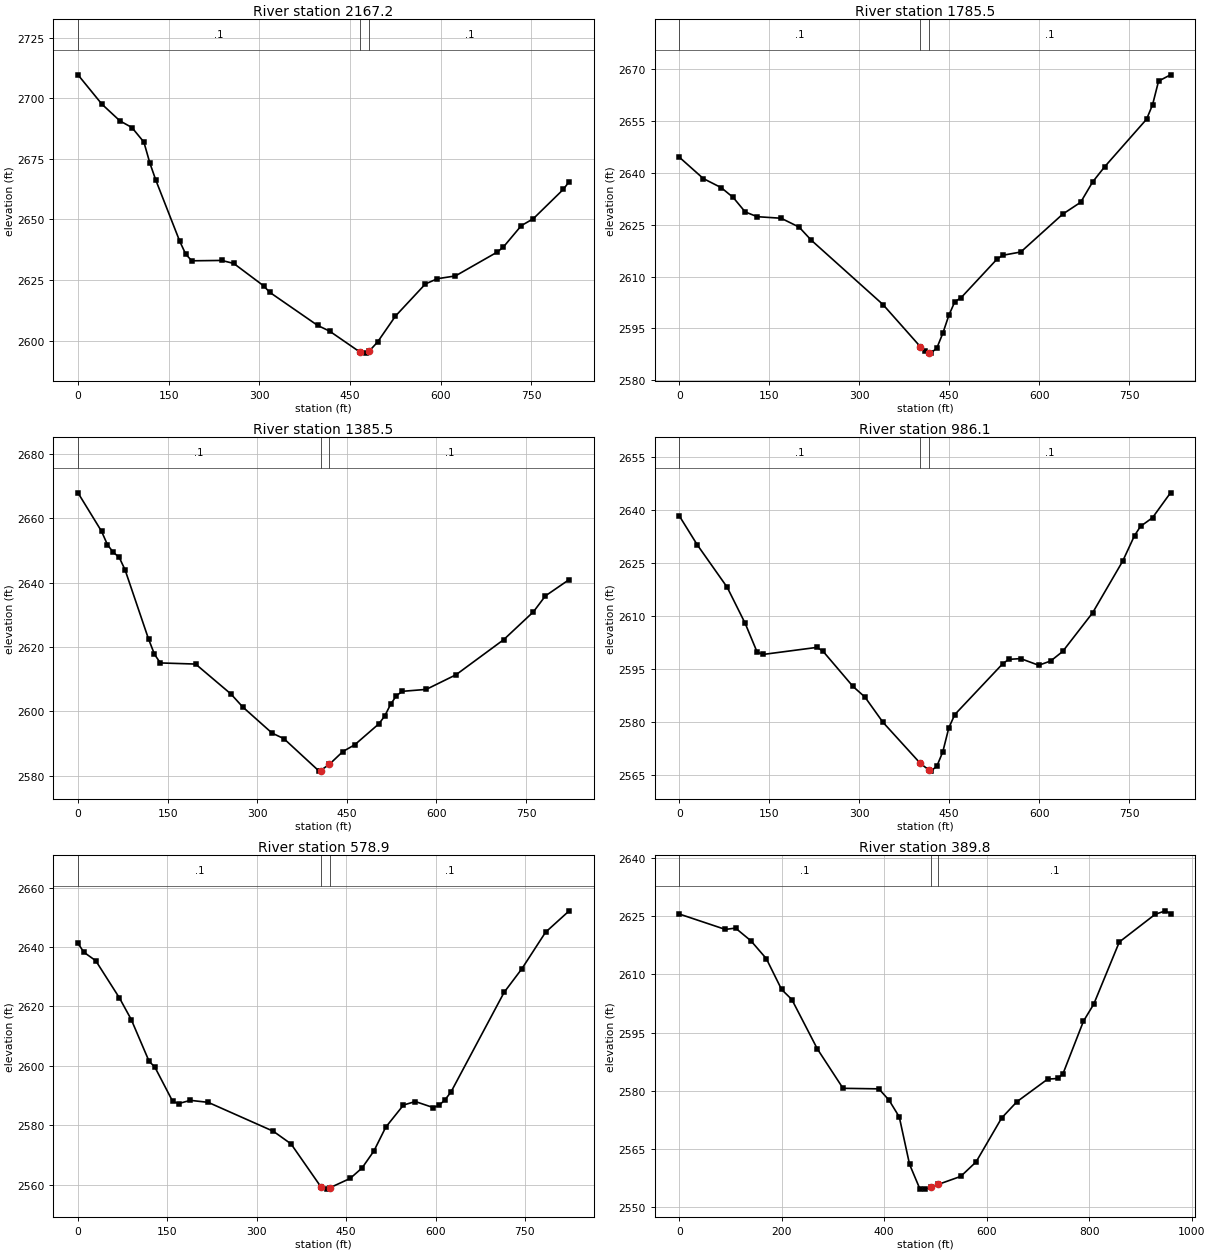
Type RM Length L Ch R = 1 ,2167.2,377.9,381.7,385.6
XS GIS Cut Line= 2
     1934798.161      244909.630     1935464.739      245374.097
#Sta/Elev= 30
       0 2709.69    39.6 2697.57    69.4 2690.68    89.2 2687.94   109.0 2681.93
   118.9 2673.25   128.8 2666.18   168.4 2640.93   178.3 2635.64   188.2 2632.94
   237.8 2633.09   257.6 2631.85   307.1 2622.59   317.0 2619.96   396.3 2606.28
   416.1 2603.92     467 2595.16   475.6 2594.84     482 2595.76   495.4 2599.41
   525.1 2610.14   574.6 2623.39   594.5 2625.56   624.2 2626.69   693.5 2636.56
   703.4 2638.59   733.2 2647.45   753.0 2650.31   802.5 2662.38   812.4 2665.61
#Mann= 3 , 0 , 0
       0     0.1       0     467   0.045       0     482     0.1       0
Bank Sta=     467,     482
Exp/Cntr=0.3,0.1

Type RM Length L Ch R = 1 ,1785.5,399.7,400,402
XS GIS Cut Line= 3
     1934659.052      245191.424     1934952.999      245476.611
     1935242.557      245766.160
#Sta/Elev= 30
       0 2644.61    40.0 2638.42    69.9 2635.78    89.9 2632.94   109.9 2628.75
   129.9 2627.37   169.8 2626.92   199.8 2624.36   219.8 2620.61   339.6 2601.94
   402.1 2589.70   409.6 2588.39   417.1 2588.00   419.5 2587.87   429.5 2589.36
   439.5 2593.68   449.5 2598.83   459.5 2602.80   469.5 2603.85   529.4 2615.02
   539.4 2616.20   569.4 2617.15   639.3 2628.11   669.2 2631.54   689.2 2637.43
   709.2 2641.82   779.1 2655.59   789.1 2659.78   799.1 2666.62   819.0 2668.44
#Mann= 3 , 0 , 0
       0     0.1       0   402.1   0.045       0   417.1     0.1       0
Bank Sta=   402.1,   417.1
Exp/Cntr=0.3,0.1

Type RM Length L Ch R = 1 ,1385.5,402.7,399.3,394.2
XS GIS Cut Line= 3
     1934381.583      245470.139     1934674.806      245761.662
     1934937.233      246075.106
#Sta/Elev= 30
       0 2667.85    39.4 2655.93    49.2 2651.80    59.1 2649.36    68.9 2647.86
    78.8 2643.96   118.1 2622.48   128.0 2617.76   137.8 2615.05   196.9 2614.70
   256.0 2605.42   275.6 2601.42   324.9 2593.27   344.6 2591.56   403.6 2581.47
     406 2581.65     421 2583.61   443.4 2587.55   463.3 2589.65   503.2 2596.07
   513.2 2598.47   523.2 2602.16   533.1 2604.91   543.1 2606.24   583.0 2606.84
   632.8 2611.38   712.6 2622.27   762.4 2630.92   782.4 2635.85   822.3 2640.93
#Mann= 3 , 0 , 0
       0     0.1       0     406   0.045       0     421     0.1       0
Bank Sta=     406,     421
Exp/Cntr=0.3,0.1

Type RM Length L Ch R = 1 ,986.1,398.1,407.2,415.8
XS GIS Cut Line= 3
     1934062.638      245799.065     1934393.505      246040.317
     1934719.507      246288.303
#Sta/Elev= 30
       0 2638.37    30.0 2630.17    79.9 2618.16   109.9 2607.95   129.8 2599.83
   139.8 2599.16   229.7 2601.16   239.7 2600.06   289.6 2590.12   309.6 2587.10
   339.6 2579.98     402 2568.34     417 2566.36   419.5 2566.15   429.5 2567.54
   439.4 2571.60   449.4 2578.36   459.4 2582.15   539.4 2596.54   549.4 2597.77
   569.3 2597.98   599.3 2596.10   619.3 2597.31   639.3 2600.00   689.2 2610.93
   739.2 2625.50   759.1 2632.78   769.1 2635.39   789.1 2637.84   819.1 2644.88
#Mann= 3 , 0 , 0
       0     0.1       0     402   0.045       0     417     0.1       0
Bank Sta=     402,     417
Exp/Cntr=0.3,0.1

Type RM Length L Ch R = 1 ,578.9,191.4,189.1,186.9
XS GIS Cut Line= 2
     1933912.559      245955.951     1934339.044      246661.357
#Sta/Elev= 30
       0 2641.25     9.9 2638.24    29.8 2635.40    69.5 2622.90    89.4 2615.61
   119.2 2601.63   129.1 2599.58   158.9 2588.10   168.8 2587.36   188.7 2588.44
   218.5 2587.77   327.7 2578.06   357.5 2573.80   408.2 2559.20   417.1 2558.59
   423.2 2559.09   456.8 2562.20   476.7 2565.71   496.6 2571.42   516.4 2579.40
   546.2 2586.87   566.1 2588.04   595.9 2586.03   605.8 2586.72   615.8 2588.63
   625.7 2591.17   715.1 2624.77   744.9 2632.70   784.6 2644.97   824.3 2652.17
#Mann= 3 , 0 , 0
       0     0.1       0   408.2   0.045       0   423.2     0.1       0
Bank Sta=   408.2,   423.2
Exp/Cntr=0.3,0.1

Type RM Length L Ch R = 1 ,389.8,400.5,389.8,379.1
XS GIS Cut Line= 2
     1933656.753      245986.188     1934234.421      246751.312
#Sta/Elev= 30
       0 2625.54    89.9 2621.57   109.8 2621.91   139.8 2618.64   169.8 2614.06
   199.7 2606.10   219.7 2603.51   269.6 2590.76   319.6 2580.64   389.5 2580.50
   409.4 2577.59   429.4 2573.26   449.4 2561.07   469.4 2554.78   479.4 2554.67
   490.5 2555.19   505.5 2555.89   549.3 2557.95   579.2 2561.67   629.2 2573.00
   659.1 2577.20   719.0 2583.01   739.0 2583.17   749.0 2584.44   788.9 2597.95
   808.9 2602.32   858.8 2618.33   928.8 2625.46   948.7 2626.36   958.7 2625.64
#Mann= 3 , 0 , 0
       0     0.1       0   490.5   0.045       0   505.5     0.1       0
Bank Sta=   490.5,   505.5
Exp/Cntr=0.3,0.1